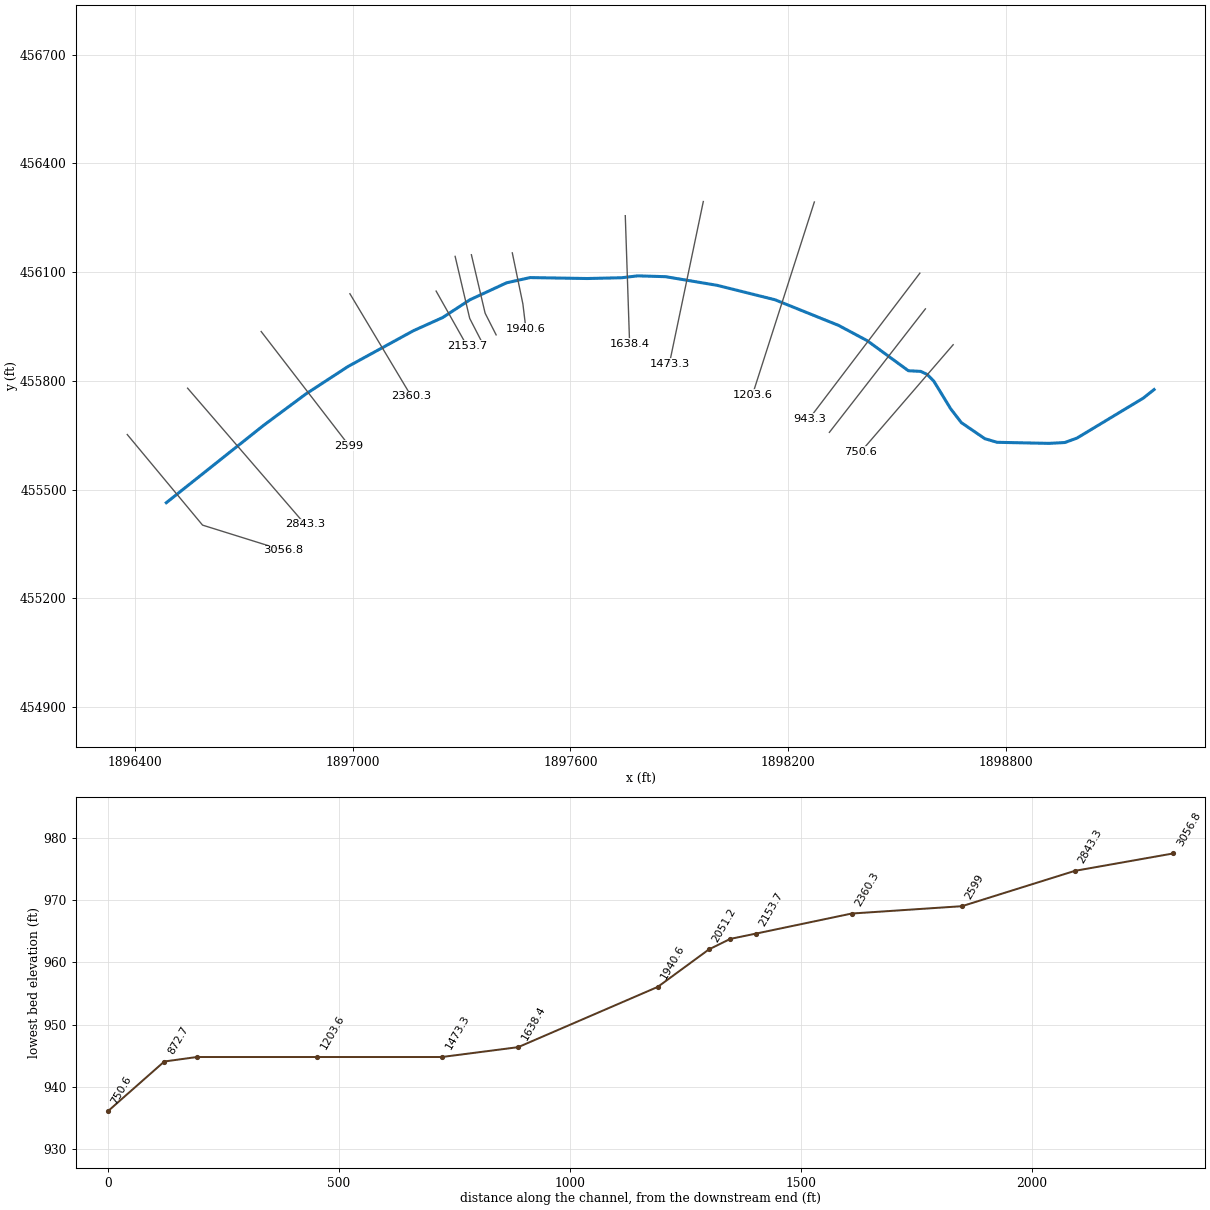
--- HUGHESFORK.prj (project) ---

Proj Title=HUGHESFORK
Current Plan=p01
Default Exp/Contr=0,0
English Units
Geom File=g01
Flow File=f01
Plan File=p01
BEGIN DESCRIPTION:
END DESCRIPTION:
DSS Export Rating Curves= 0
DSS Export Rating Curve Sorted= 0
DSS Export Volume Flow Curves= 0
DXF OffsetX= 0
DXF OffsetY= 0
DXF ScaleX= 0
DXF ScaleY= 0

--- HUGHESFORK.p01 (plan) ---

Plan Title=Floodplain
Program Version=4.00
Geom File=g01
Flow File=f01
K Sum by GR=0
Std Step Tol=0.01
Critical Tol=0.01
Num of Std Step Trials=20
Max Error Tol=0.3
Flow Tol Ratio=0.001
Split Flow NTrial=30
Split Flow Tol=0.02
Split Flow Ratio=0.02
Log Output Level=0
Friction Slope Method=1
Unsteady Friction Slope Method=2
Unsteady Bridges Friction Slope Method=1
Global Log Level=0
CheckData=False
Run HTab=0
Run UNet=0
Run PostProcess=0
UNET Theta=0
UNET Theta Warmup=0
UNET ZTol=0
UNET ZSATol=0
UNET MxIter=0
UNET MaxInSteps=0
UNET DtIC=0
UNET DtMin=0
UNET MaxCRTS=0
UNET WFStab=0
UNET SFStab=0
UNET WFX=0
UNET SFX=0
UNET DSS MLevel=0
UNET DZMax Abort=0
UNET Convert EG Bridges=0
UNET Use Existing IB Tables=0
UNET Froude Limit=0
UNET Froude Power=0
Write IC File=0
Echo Input=False
Echo Output=False
Write Detailed=0

--- HUGHESFORK.f01 (steady flow) ---

Flow Title=NFF Regression Equation
Program Version=4.10
Number of Profiles= 1
Profile Names=P100yr
River Rch & RM=HUGHESFORK,Main            ,3056.8
814.0503
Boundary for River Rch & Prof#=HUGHESFORK,Main            , 1
Up Type= 0
Dn Type= 3
Dn Slope=0.032
DSS Import GetInterval= 0
DSS Import GetPeak= 0
DSS Import FillOption= 0

--- HUGHESFORK.g01 (geometry) ---

Geom Title=USGS 10m DEM
Program Version=4.10

River Reach=HUGHESFORK      ,Main
Reach XY= 30
     1896487.112      455463.804     1896755.237      455677.449
      1896871.02      455763.572     1896987.533        455839.7
     1897167.494       455938.37     1897248.223      455974.828
      1897323.31      456023.873     1897424.439      456070.748
     1897489.109      456085.071     1897645.793      456082.467
     1897741.279      456084.637     1897785.116      456089.845
     1897862.014      456087.543     1898003.713      456063.735
     1898163.289      456023.877     1898338.556      455953.052
     1898417.405      455910.865     1898530.686      455827.966
      1898564.54       455826.23     1898582.518      455817.734
      1898600.69      455799.238     1898647.092      455722.983
     1898676.545      455684.764     1898741.259      455640.453
     1898774.871      455630.535     1898917.947      455627.551
     1898961.394       455629.94     1898994.845      455642.123
     1899177.021      455752.115     1899207.203      455776.053

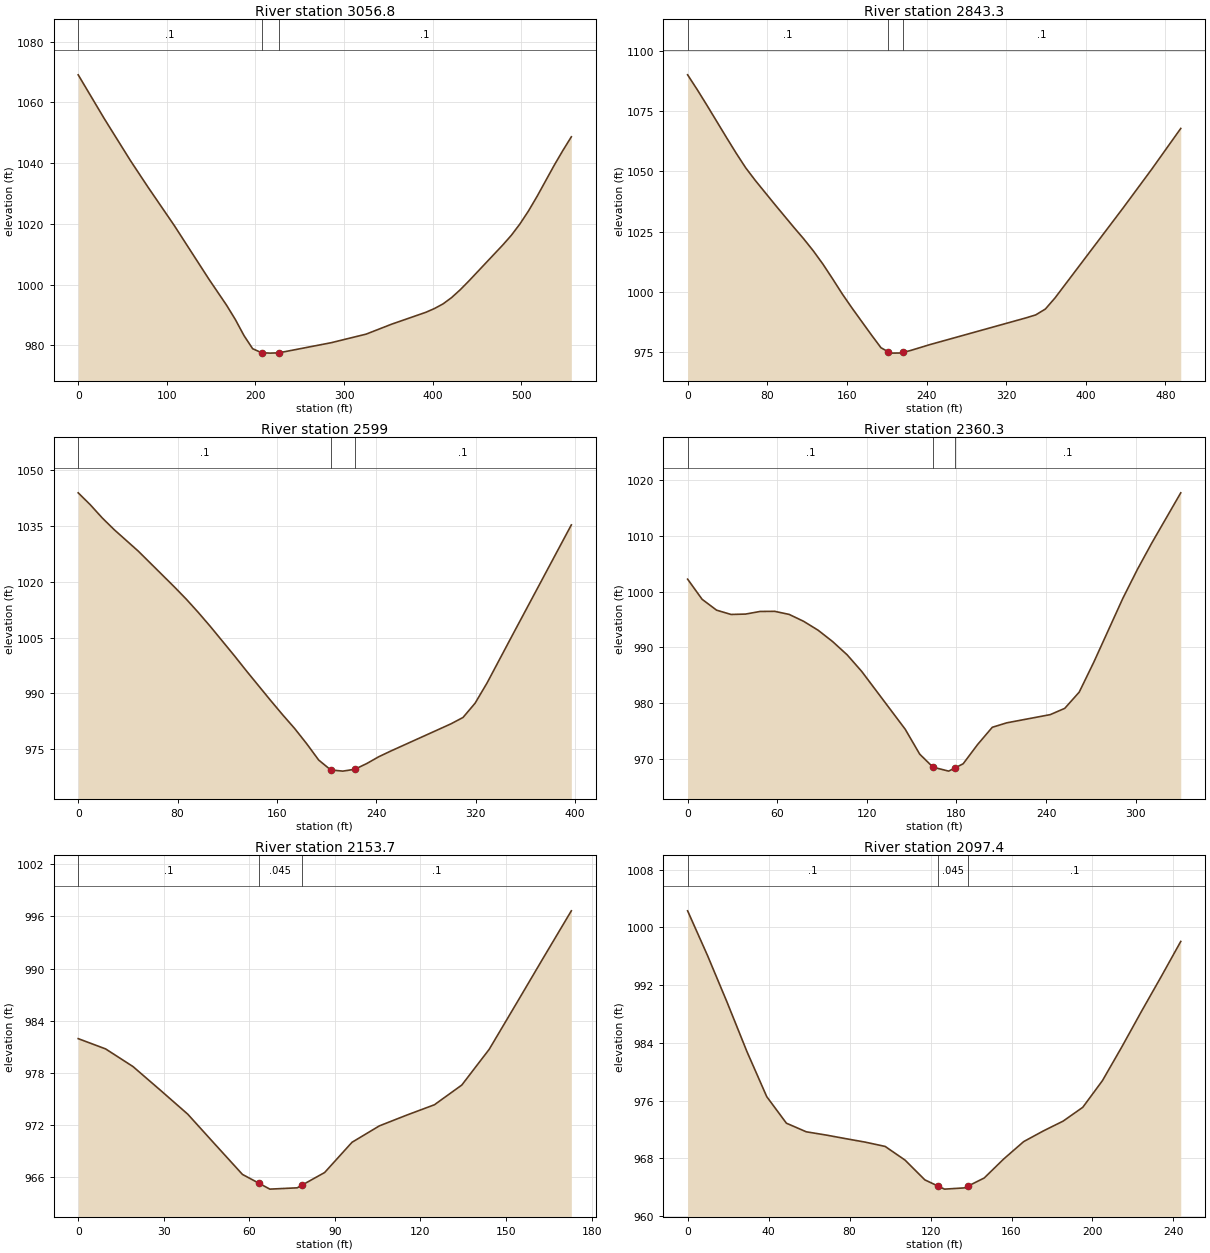
Type RM Length L Ch R = 1 ,3056.8  ,213,213.4,213.8
XS GIS Cut Line= 3
     1896379.597      455651.955     1896586.958      455401.988
     1896807.864       455332.84
#Sta/Elev= 30
       0 1069.07    29.5 1054.61      59 1040.81    78.7 1032.13   108.3 1019.51
   147.6 1001.75   167.3  993.28   177.2  988.57     187  983.26   196.8  978.92
   206.8  977.62   216.5  977.47   226.4  977.57   285.4   980.9   324.8  983.72
   353.7  987.01   392.3  990.92   401.9  992.15   411.6  993.68   421.2  995.74
   430.9  998.31   440.5 1001.15   479.1  1013.1   488.7 1016.28   498.4 1020.03
     508 1024.28   517.7 1029.09     537 1039.31   546.6 1044.09   556.3 1048.67
#Mann= 3 , 0 , 0
       0      .1       0   206.8    .045       0   226.4      .1       0
Bank Sta=206.8,226.4
XS Rating Curve= 0 ,0
Exp/Cntr=0.3,0.1

Type RM Length L Ch R = 1 ,2843.3  ,245.6,244.4,243.1
XS GIS Cut Line= 2
     1896545.759      455779.879     1896869.045       455404.45
#Sta/Elev= 30
       0 1089.94     9.7 1083.78    19.4 1077.34    38.9 1064.08    48.6  1057.6
    58.3 1051.46      68 1046.19    87.4 1036.36   106.9 1026.68   116.6 1022.02
   126.3 1017.01     136 1011.49   145.7 1005.42   155.4  999.16   165.2  993.32
   184.6  982.23   194.3  976.88   201.3  975.29     204  974.67   213.7  974.72
   216.3  974.98   223.4  975.69   242.9  978.14     340  989.28   349.7   990.5
   359.4  992.93   369.2  997.59   437.2 1034.64   466.3 1050.88   495.4 1067.74
#Mann= 3 , 0 , 0
       0      .1       0   201.3    .045       0   216.3      .1       0
Bank Sta=201.3,216.3
XS Rating Curve= 0 ,0
Exp/Cntr=0.3,0.1

Type RM Length L Ch R = 1 ,2599    ,241.2,238.7,236
XS GIS Cut Line= 2
     1896748.334      455936.238     1896990.305      455621.568
#Sta/Elev= 28
       0 1043.98     9.7 1040.78    19.4  1037.2      29 1034.05    48.4 1028.26
    77.4 1018.64    87.1  1015.3    96.8 1011.71   106.5 1007.93   125.9 1000.02
   135.5  995.98   154.9  988.04   164.6  984.18   174.3  980.47     184  976.36
   193.6  971.99   203.3  969.33     213     969   222.7   969.5   232.4  971.06
     242  972.88   251.7  974.42   300.1  981.74   309.8  983.46   319.5  987.29
   329.2  992.78   348.5 1004.96     397 1035.34
#Mann= 3 , 0 , 0
       0      .1       0   203.3    .045       0   222.7      .1       0
Bank Sta=203.3,222.7
XS Rating Curve= 0 ,0
Exp/Cntr=0.3,0.1

Type RM Length L Ch R = 1 ,2360.3  ,207,206.5,205.8
XS GIS Cut Line= 2
     1896992.736      456040.465     1897162.112       455756.99
#Sta/Elev= 30
       0 1002.24     9.7  998.63    19.4  996.68    29.1  995.91    38.8  995.98
    48.6  996.45    58.3  996.47      68  995.92    77.7  994.68    87.4  993.08
    97.1  991.05   106.8  988.68   116.6  985.69   145.7  975.33   155.4  970.87
   164.3  968.53   174.8  967.82   179.3  968.43   184.5  969.14   194.2   972.6
     204  975.68   213.7  976.48   242.8  977.95   252.5  979.07   262.2  981.98
     272  987.37   291.4  998.79   301.1 1003.95   310.8 1008.72   330.2 1017.72
#Mann= 3 , 0 , 0
       0      .1       0   164.3    .045       0   179.3      .1       0
Bank Sta=164.3,179.3
XS Rating Curve= 0 ,0
Exp/Cntr=0.3,0.1

Type RM Length L Ch R = 1 ,2153.7  ,63.1,56.3,49.7
XS GIS Cut Line= 2
     1897230.171      456047.769     1897314.893      455897.074
#Sta/Elev= 21
       0  981.93     9.6  980.75    19.2  978.72    28.8     976    38.4  973.24
      48  969.76    57.6   966.3    63.3   965.3    67.2  964.61    76.8  964.76
    78.3  965.04    86.4  966.52      96     970   105.6  971.89   115.2  973.13
   124.9  974.32   134.5  976.59   144.1   980.7   153.7  986.01   163.3  991.35
   172.9  996.64
#Mann= 3 , 0 , 0
       0      .1       0    63.3    .045       0    78.3      .1       0
Bank Sta=63.3,78.3
XS Rating Curve= 0 ,0
Exp/Cntr=0.3,0.1

Type RM Length L Ch R = 1 ,2097.4  ,45.8,46.2,46.4
XS GIS Cut Line= 3
     1897282.494      456143.598     1897322.582      455972.472
     1897353.618       455912.09
#Sta/Elev= 28
       0 1002.29     9.8  996.12    19.5  989.63    29.3   982.8    39.1  976.55
    48.8  972.88    58.6  971.69    68.4  971.24    78.1  970.74    87.9  970.25
    97.6  969.66   107.4  967.77   117.2  965.03   123.5   964.2   126.9  963.75
   136.7  963.92   138.5  964.17   146.5  965.29   156.2  967.94     166  970.33
   175.8  971.82   185.5  973.17   195.2  975.08   204.9  978.77   214.6   983.5
   224.2  988.37     234  993.21   243.6  998.05
#Mann= 3 , 0 , 0
       0      .1       0   123.5    .045       0   138.5      .1       0
Bank Sta=123.5,138.5
XS Rating Curve= 0 ,0
Exp/Cntr=0.3,0.1

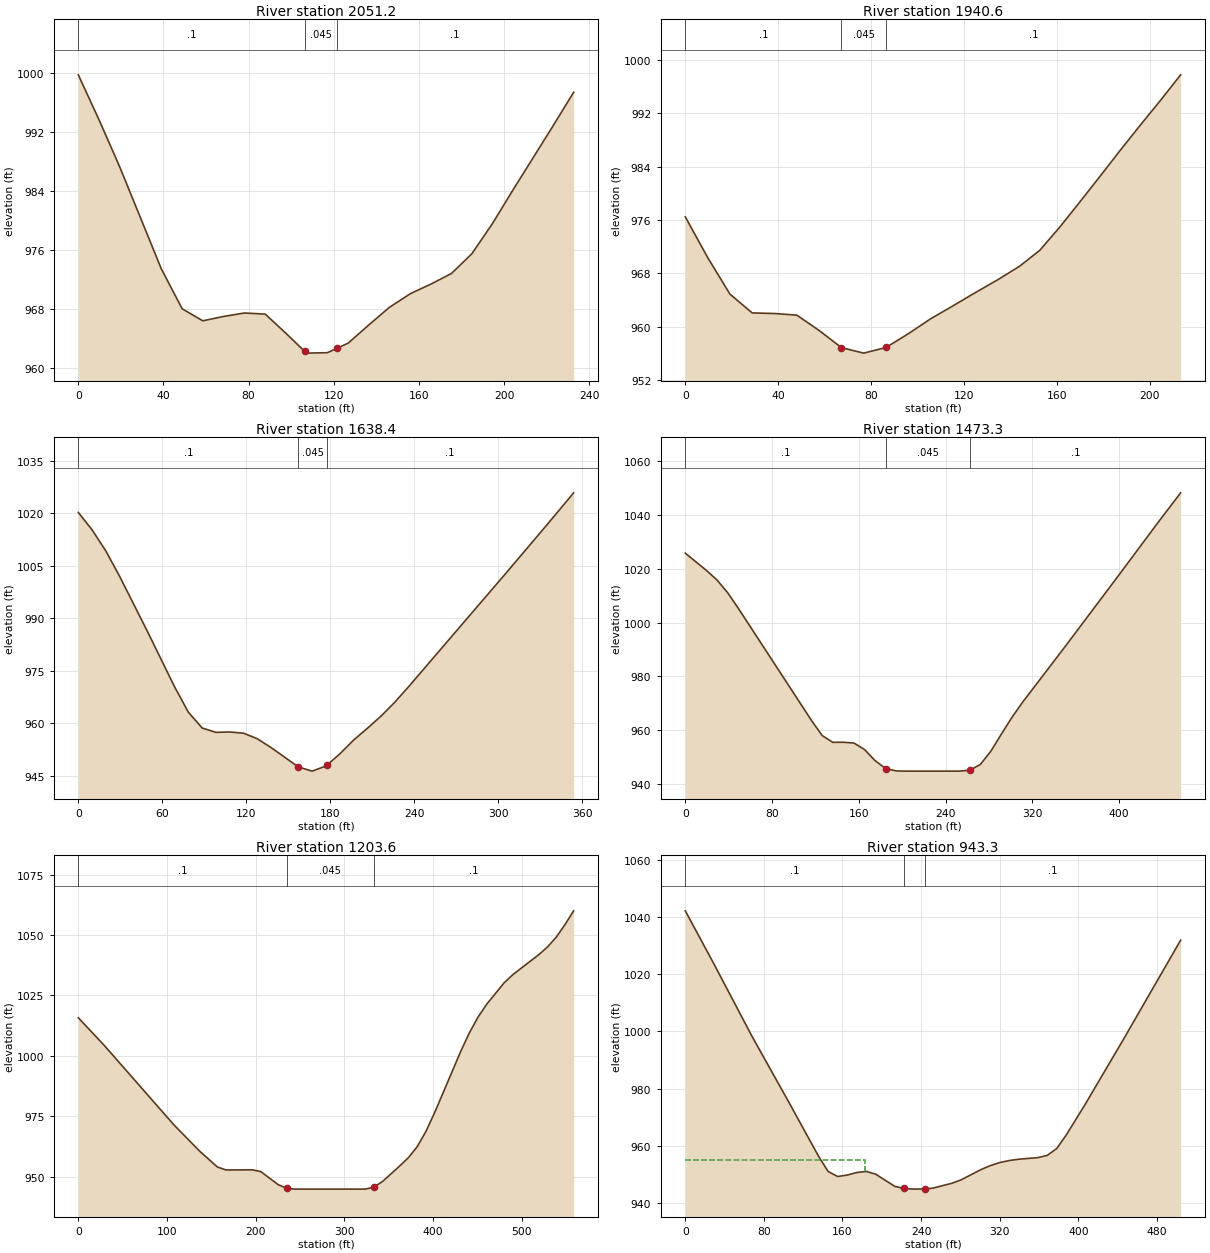
Type RM Length L Ch R = 1 ,2051.2  ,111,110.6,109.9
XS GIS Cut Line= 3
     1897327.262      456148.133     1897365.066      455986.754
     1897395.367      455927.006
#Sta/Elev= 27
       0  999.79     9.8  993.65    19.5  987.28    29.2  980.42      39  973.48
    48.8  968.07    58.5  966.44    68.2  967.03      78   967.5    87.8  967.35
    97.5  964.76   106.3  962.31   107.2  962.06     117  962.12   121.3  962.69
   126.8  963.42   136.5  965.89   146.2  968.28     156  970.12   165.8  971.44
   175.3  972.86   184.9  975.54   194.5   979.6     204  984.09   213.6  988.52
   223.2  992.95   232.7  997.43
#Mann= 3 , 0 , 0
       0      .1       0   106.3    .045       0   121.3      .1       0
Bank Sta=106.3,121.3
XS Rating Curve= 0 ,0
Exp/Cntr=0.3,0.1

Type RM Length L Ch R = 1 ,1940.6  ,306,302.2,298.3
XS GIS Cut Line= 3
     1897439.893      456153.324     1897469.059      456012.352
     1897477.393      455943.602
#Sta/Elev= 26
       0  976.49     9.6  970.41    19.2  964.91    28.8  962.08    38.4  961.99
      48  961.75    57.6  959.45    67.2  956.88    68.7  956.75    76.8  956.05
    83.7  956.66    86.4   956.9      96  958.96   105.6   961.2   115.2  963.14
   124.8  965.12   134.4  967.04     144  969.11   152.6  971.48   161.3     975
   169.9  978.76   178.6  982.61   187.2  986.47   195.9  990.27   204.6  993.99
   213.2  997.79
#Mann= 3 , 0 , 0
       0      .1       0    67.2    .045       0    86.4      .1       0
Bank Sta=67.2,86.4
XS Rating Curve= 0 ,0
Exp/Cntr=0.3,0.1

Type RM Length L Ch R = 1 ,1638.4  ,170.2,165.1,159.4
XS GIS Cut Line= 2
     1897751.038      456255.872     1897762.974      455902.139
#Sta/Elev= 26
       0 1020.26     9.8 1015.31    19.7 1009.24    29.5 1002.03    49.2  986.42
    68.8  970.46    78.6  963.22    88.5  958.69    98.3  957.46   108.2  957.55
     118  957.22   127.8  955.64   137.6  953.15   157.3  947.55   167.1  946.38
     177  947.86   177.5  948.04   186.8  951.29   196.6  955.21   206.5   958.6
   216.3   962.1   226.1  966.05     236   970.5   304.8 1002.57   334.3 1016.48
   353.9 1025.86
#Mann= 3 , 0 , 0
       0      .1       0   157.3    .045       0   177.5      .1       0
Bank Sta=157.3,177.5
XS Rating Curve= 0 ,0
Exp/Cntr=0.3,0.1

Type RM Length L Ch R = 1 ,1473.3  ,272.1,269.8,267.4
XS GIS Cut Line= 2
     1897965.882      456294.934     1897872.566      455847.886
#Sta/Elev= 26
       0 1025.83    19.4 1019.44    29.2 1015.88    38.9 1011.21    48.6 1005.51
   116.6  963.48   126.3     958     136   955.5   145.8  955.54   155.5  955.24
   165.2  952.85   174.9  948.74  184.63  945.77  194.55  944.87     204   944.8
   252.6   944.8   262.4  945.12   272.1  947.31   281.8  952.26   291.5  958.62
   301.2  964.81   310.9  970.37   349.8   990.9   398.4 1016.96   437.2 1037.96
   456.7 1048.26
#Mann= 3 , 0 , 0
       0      .1       0  184.63    .045       0   262.4      .1       0
Bank Sta=184.63,262.4
XS Rating Curve= 0 ,0
Exp/Cntr=0.3,0.1

Type RM Length L Ch R = 1 ,1203.6  ,267.9,260.3,252.6
XS GIS Cut Line= 2
     1898271.679      456293.737     1898101.275      455761.661
#Sta/Elev= 30
       0 1015.77    29.4 1004.27   107.8  971.42   137.2  960.42   156.8  953.98
   166.6  952.73     196   952.8   205.8  952.08   225.4  946.67   235.2  945.11
     245   944.8   323.5   944.8   333.3  945.59   343.1  947.96   362.7  954.46
   372.5   957.9   382.3   962.4   392.1  968.73   401.9  976.47   431.3 1001.82
   441.1 1009.53   450.9 1016.06   460.7 1021.41   480.3 1030.24   490.1 1033.63
   519.5 1041.93   529.3 1045.13   539.1 1049.16   548.9 1054.34   558.7 1060.05
#Mann= 3 , 0 , 0
       0      .1       0   235.2    .045       0   333.3      .1       0
Bank Sta=235.2,333.3
XS Rating Curve= 0 ,0
Exp/Cntr=0.3,0.1

Type RM Length L Ch R = 1 ,943.3   ,70.8,70.6,70.3
XS GIS Cut Line= 2
     1898562.251       456097.34     1898257.557      455695.632
#Sta/Elev= 30
       0  1042.2    29.1 1023.65    67.9  998.28   106.7  974.42   135.7  956.27
   145.4  950.98   155.1  949.21   164.8  949.72   174.5  950.61   184.2  950.99
   193.9  950.02   213.3  945.76     223  945.02   232.7   944.8   243.6  944.88
   252.1  945.16   271.5  946.86   281.2  948.12   300.6  951.59   310.3  953.01
     320  954.09   329.7   954.8   339.4  955.27   358.8  955.82   368.4   956.6
   378.1  959.02   387.8  963.76   407.2  974.57     446  997.22   504.2 1031.93
#Mann= 3 , 0 , 0
       0      .1       0     223    .045       0   243.6      .1       0
#XS Ineff= 2 , 0
          182.82     955
Permanent Ineff=
       F       F
Bank Sta=223,243.6
XS Rating Curve= 0 ,0
Exp/Cntr=0.3,0.1

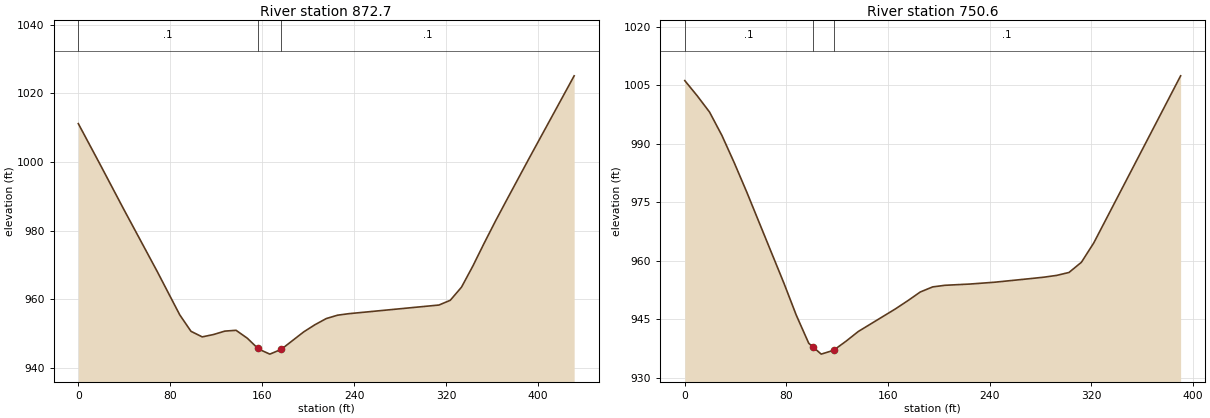
Type RM Length L Ch R = 1 ,872.7   ,123,122.1,121.2
XS GIS Cut Line= 2
     1898577.476      455998.746      1898313.05      455657.971
#Sta/Elev= 29
       0  1011.2    19.6  998.91    39.2  986.46    68.6  968.16    88.2  955.53
      98  950.72   107.8   949.1   117.6  949.79   127.4  950.78   137.2  951.02
     147  948.71     156  945.81   156.8  945.55   166.6  944.08   176.4  945.45
   196.1  950.57   205.9  952.66   215.7  954.44   225.5  955.42   235.3  955.86
   313.7  958.38   323.5  959.75   333.3  963.58   343.1  969.68   352.9  976.31
   362.7  982.73   372.5   988.9   392.1 1001.09   431.3 1025.13
#Mann= 3 , 0 , 0
       0      .1       0     156    .045       0   176.4      .1       0
Bank Sta=156,176.4
XS Rating Curve= 0 ,0
Exp/Cntr=0.3,0.1

Type RM Length L Ch R = 1 ,750.6   ,718.9,750.6,781.3
XS GIS Cut Line= 2
     1898653.946      455899.795     1898399.259      455603.962
#Sta/Elev= 28
       0 1006.23     9.8 1002.33    19.5  998.16    29.3  992.12      39  985.12
    48.8  977.64    78.1  954.25    87.8  946.07    97.6  938.88   101.3  937.83
   107.4   936.1   117.1  937.08   126.9   939.4   136.6   941.9   165.9  947.71
   175.7  949.82   185.4  952.03   195.2  953.34   204.9  953.75   224.5  954.07
     244  954.54   273.2   955.5     283  955.84   292.8  956.29   302.5  957.04
   312.3  959.66     322  964.61   390.4 1007.46
#Mann= 3 , 0 , 0
       0      .1       0   101.3    .045       0   117.1      .1       0
Bank Sta=101.3,117.1
XS Rating Curve= 0 ,0
Exp/Cntr=0.3,0.1

Chan Stop Cuts=-1
Use User Specified Reach Order=0
Composite Channel Slope=5